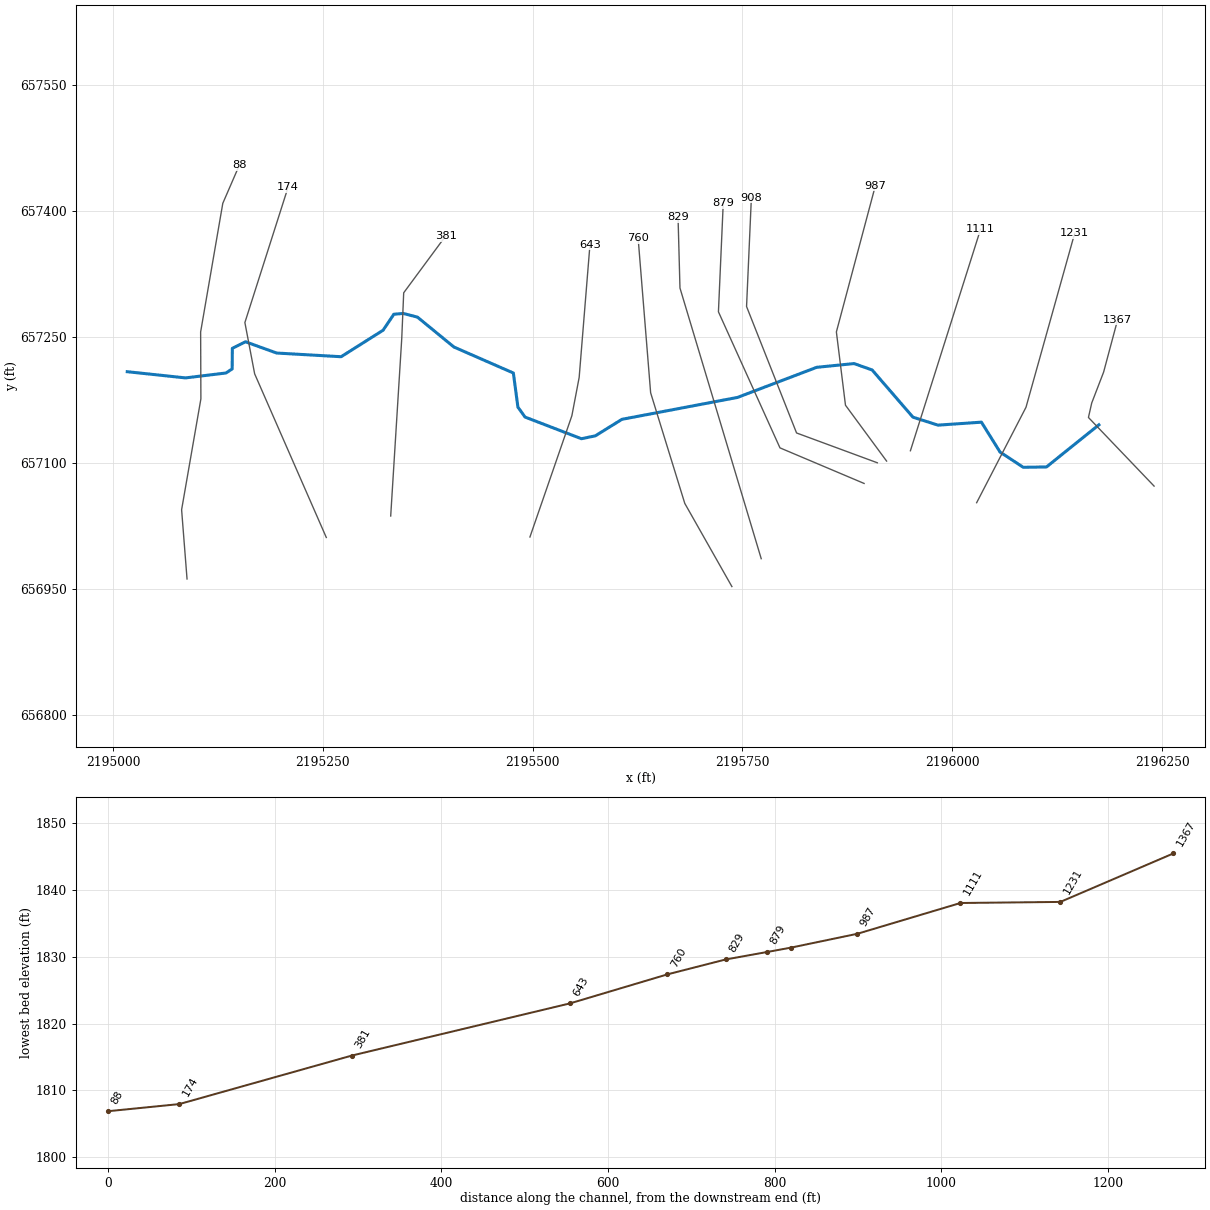
--- SWAMPRN1.prj (project) ---

Proj Title=SWAMPRN1
Current Plan=p01
Default Exp/Contr=0,0
English Units
Geom File=g01
Flow File=f01
Plan File=p01
BEGIN DESCRIPTION:
---------- MODELED AS PART OF WVEMD CTP PROGRAM, 2023----------
Stream Name: Swamp Run
Flood Zone:  AFH
Upshur County, WV
HEC-RAS Version: RAS 6.3
Vertical Datum: NAVD88
Projection: NAD 1983 StatePlane West Virginia S FIPS 4702 (US Feet)
Terrain: 1-meter LIDAR (FEMA Region III 3DEP collected 2016-2018)
Land Use: 2019 NLCD
Hydrologic Method:
WV SIR2010-5033 regression equations
Additional Model Notes:
None
END DESCRIPTION:
DSS File=dss
DSS Export Rating Curves= 0
DSS Export Rating Curve Sorted= 0
DSS Export Volume Flow Curves= 0
DXF OffsetX= 0
DXF OffsetY= 0
DXF ScaleX= 0
DXF ScaleY= 0

--- SWAMPRN1.p01 (plan) ---

Plan Title=Floodplain
Program Version=6.30
Short Identifier=Floodplain
Geom File=g01
Flow File=f01
Subcritical Flow
K Sum by GR= 0
Std Step Tol= 0.01
Critical Tol= 0.01
Num of Std Step Trials= 20
Max Error Tol= 0.3
Flow Tol Ratio= 0.001
Split Flow NTrial= 30
Split Flow Tol= 0.02
Split Flow Ratio= 0.02
Log Output Level= 0
Friction Slope Method= 1
Unsteady Friction Slope Method= 2
Unsteady Bridges Friction Slope Method= 1
Parabolic Critical Depth
Global Vel Dist= 0 , 0 , 0
Global Log Level= 0
CheckData=False
Encroach Param=-1 ,0,0, 0
Computation Interval=0.1SEC
Output Interval=1SEC
Instantaneous Interval=Max Profile
Mapping Interval=1HOUR
Computation Time Step Use Courant=        0
Computation Time Step Use Time Series=    0
Computation Time Step Count To Double=0
Computation Time Step Max Doubling=0
Computation Time Step Max Halving=0
Computation Time Step Residence Courant=0
Run HTab= 0
Run UNet= 0
Run Sediment= 0
Run PostProcess= 0
Run WQNet= 0
Run RASMapper=-1
UNET Theta= 0
UNET Theta Warmup= 0
UNET ZTol= 0
UNET ZSATol= 0
UNET MxIter= 0
UNET Max Iter WO Improvement= 0
UNET MaxInSteps= 0
UNET DtIC= 0
UNET DtMin= 0
UNET MaxCRTS= 0
UNET WFStab= 0
UNET SFStab= 0
UNET WFX= 1
UNET SFX= 1
UNET Gravity=32.17405
UNET 1D Methodology=Finite Difference
UNET DSS MLevel= 1
UNET Pardiso=0
UNET DZMax Abort= 0
UNET Use Existing IB Tables= 0
UNET Froude Reduction=False
UNET Froude Limit= 0
UNET Froude Power= 0
UNET D1 Cores= 0
UNET WindReference=Eulerian
UNET WindDragFormulation=Hsu (1988)
UNET D2 Coriolis=0
UNET D2 Cores= 0
UNET D2 Theta= 1
UNET D2 Theta Warmup= 1
UNET D2 Z Tol= 0.01
UNET D2 Volume Tol= 0.01
UNET D2 Max Iterations= 20
UNET D2 Equation= 0
UNET D2 RampUpFraction=0.1
UNET D2 TimeSlices= 1
UNET D2 Turbulence Formulation=Non-Conservative (original)
UNET D2 Eddy Viscosity=0.3
UNET D2 Transverse Eddy Viscosity=0.1
UNET D2 Smagorinsky Mixing=0
UNET D2 BCVolumeCheck=0
UNET D2 Cores=0
UNET D2 SolverType=PARDISO (Direct)
UNET D2 Minimum Iterations= 3
UNET D2 Maximum Iterations= 30
UNET D2 Restart Number= 10
UNET D2 Relaxation Coeff=1.3
UNET D2 SOR Precondition Iterations= 10
UNET D2 ILUT Maximum Fill= 8
UNET D2 ILUT Tolerance=1E-08
UNET D2 Convergence Tolerance=0.00001
UNET D1D2 MaxIter= 0
UNET D1D2 ZTol=0.01
UNET D1D2 QTol=0.1
UNET D1D2 MinQTol=1
DSS File=dss
Write IC File= 0
Write IC File at Fixed DateTime=0
Write IC File at Sim End=0
Echo Input=False
Echo Parameters=False
Echo Output=False
Write Detailed= 0
HDF Write Warmup=0
HDF Write Time Slices=0
HDF Flush=0
HDF Compression= 1
HDF Chunk Size= 1
HDF Spatial Parts= 1
HDF Use Max Rows=0
HDF Fixed Rows= 1
Calibration Method= 0
Calibration Iterations= 20
Calibration Max Change=0.05
Calibration Tolerance=0.2
Calibration Maximum=1.5
Calibration Minimum=0.5
Calibration Optimization Method= 1
WQ AD Non Conservative
WQ ULTIMATE=-1
WQ Max Comp Step=1HOUR
WQ Output Interval=15MIN
WQ Output Selected Increments= 0
WQ Output face flow=0
WQ Output face velocity=0
WQ Output face area=0
WQ Output face dispersion=0
WQ Output cell volume=0
WQ Output cell surface area=0
WQ Output cell continuity=0
WQ Output cumulative cell continuity=0
WQ Output face conc=0
WQ Output face dconc_dx=0
WQ Output face courant=0
WQ Output face peclet=0
WQ Output face adv mass=0
WQ Output face disp mass=0
WQ Output cell mass=0
WQ Output cell source sink temp=0
WQ Output nsm pathways=0
WQ Output nsm derived pathways=0
WQ Create Restart=0
WQ Fixed Restart=0
WQ System Summary=0
WQ Write To DSS=0
Sorting and Armoring Iterations= 10
XS Update Threshold= 0.02
Bed Roughness Predictor= 0
Hydraulics Update Threshold= 0.02
Energy Slope Method= 1
Volume Change Method= 1
Sediment Retention Method= 0
Sediment TS Multiplier= 1
Warm Up Method= 0
XS Weighting Method= 0
Number of US Weighted Cross Sections= 1
Number of DS Weighted Cross Sections= 1
Upstream XS Weight=0
Main XS Weight=1
Downstream XS Weight=0
Number of DS XS's Weighted with US Boundary= 1
Upstream Boundary Weight= 1
Weight of XSs Associated with US Boundary= 0
Number of US XS's Weighted with DS Boundary= 1
Downstream Boundary Weight= 0.5
Weight of XSs Associated with DS Boundary= 0.5
Percentile Method= 0
Sediment Output Level= 3
Mass or Volume Output= 0
Output Increment Type= 1
Profile and TS Output Increment= 1
Transport Output Increment 1
XS Output Flag= 0
XS Output Increment= 10
Read HDF5 Sediment Hotstart= 0
Sediment Hotstart Type= 0
Write Gradation File= 0
Read Gradation Hotstart= 0
Write HDF5 File= 1
Write Binary Output= 1
Write DSS Sediment File= 0
DSS Sediment Output Type= 1
SV Curve= 0
Specific Gage Flag= 0
Subcell Erosion Methods= 0
Subcell Deposition Methods= 0
Advection Scheme= 1
Matrix Solver= 0
Implicit Weighting Factor= 1
Maximum Outer Loop Convergence Iterations= 5
Convergence Maximum Absolute= 0.001
Convergence RMSE= 0.0001
Grain Fractions Max Abs Error= 0.001
Max Subgrid Regions= 1
Max Subgrid Length Scale= 3.402823E+38
Initial Layer Thickness= 3.402823E+38
Min Layer Thickness= 3.402823E+38
Max Layer Thickness= 3.402823E+38
Number of Layers= 5

--- SWAMPRN1.f01 (steady flow) ---

Flow Title=Flows
Program Version=6.31
Number of Profiles= 1
Profile Names=01pct
River Rch & RM=SWAMPRN1,Main            ,1367
     349
Boundary for River Rch & Prof#=SWAMPRN1,Main            , 1
Up Type= 0
Dn Type= 3
Dn Slope=0.01234
DSS Import GetInterval= 0
DSS Import GetPeak= 0
DSS Import FillOption= 0

--- SWAMPRN1.g01 (geometry) ---

Geom Title=Geometry
Program Version=6.31

River Reach=SWAMPRN1        ,Main
Reach XY= 30
     2196174.784      657145.723     2196112.314      657095.502
     2196084.642      657095.101      2196056.97      657113.301
     2196034.821      657148.871     2195983.025      657145.323
     2195953.207      657154.823     2195904.616      657211.055
      2195883.04      657218.695     2195838.484      657214.202
     2195744.193      657178.3462195606.50927928657152.246630326
2195574.79844516657132.5834773922195558.28468607657129.134401125
 2195491.0630875657154.928931816 2195482.5468498657166.800051028
2195477.12742582657207.445730941     2195406.291      657238.412
     2195362.851      657274.039     2195345.996      657278.389
      2195334.75      657277.473     2195321.929      657258.415
     2195271.937      657226.851     2195195.102      657231.229
     2195157.929       657244.65     2195142.304      657236.838
     2195142.133      657212.371     2195134.807      657207.478
     2195086.502      657201.611     2195017.108      657208.994

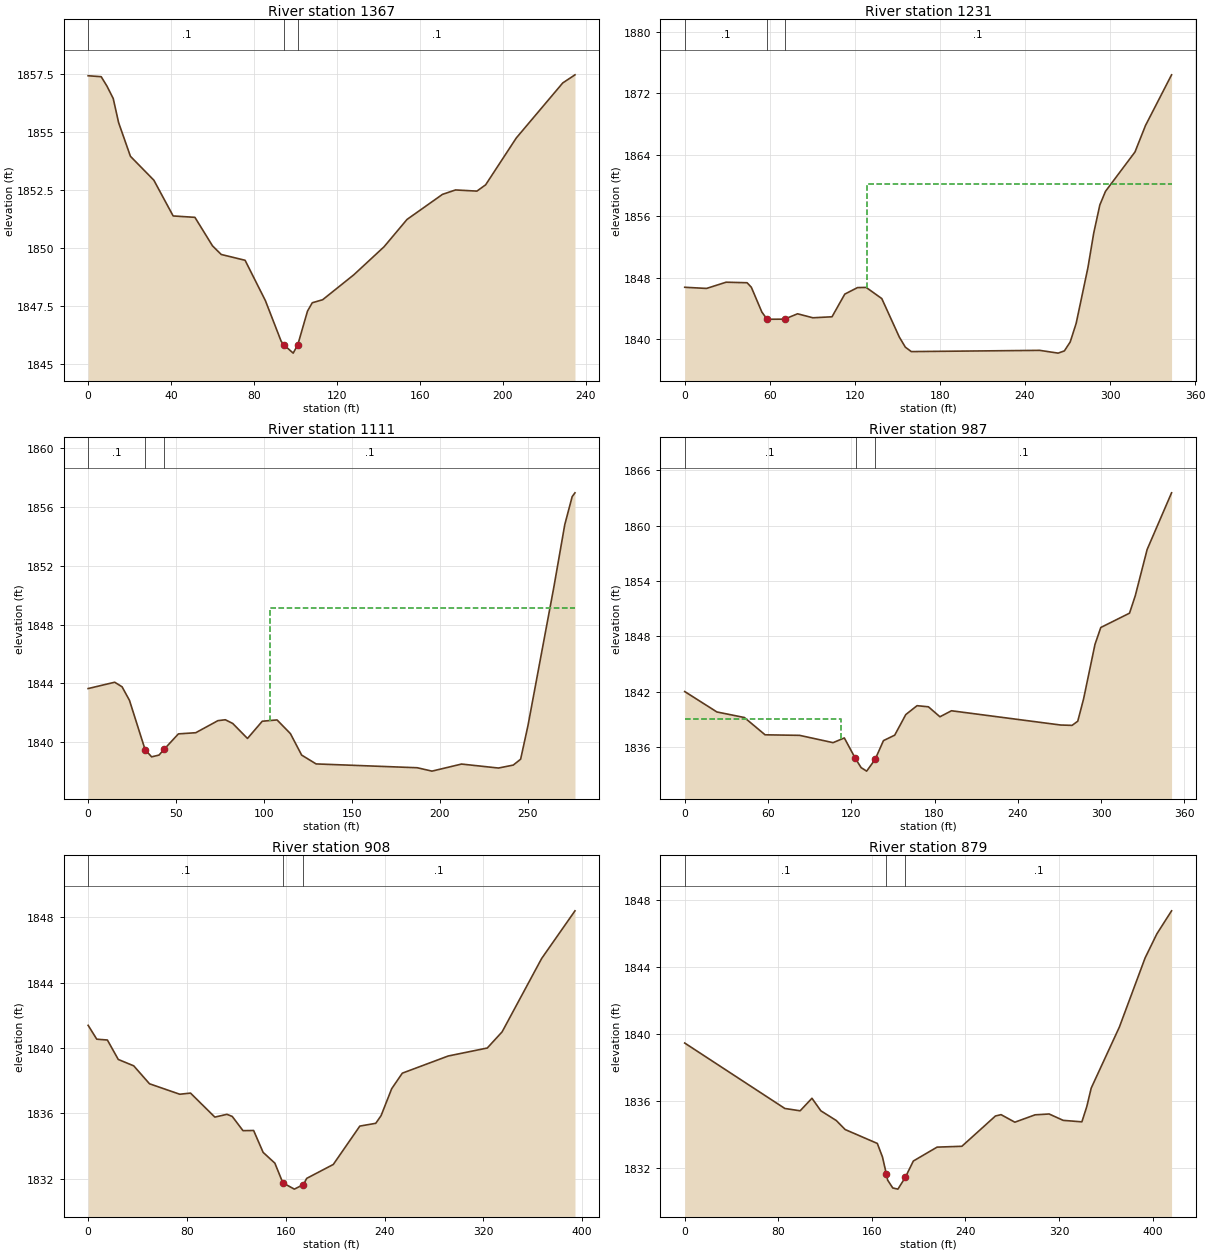
Type RM Length L Ch R = 1 ,1367    ,135.7,135.7,135.7
XS GIS Cut Line= 5
2196240.52316349 657072.706871682196162.31391599 657154.47259547
2196166.23910252657171.7334990532196180.38867537 657208.47181664
2196197.10506987657270.885792461
#Sta/Elev= 30
       0 1857.41     6.3 1857.37     9.1 1856.96    12.1 1856.43    14.7 1855.39
    20.4 1853.94    31.7 1852.91      41 1851.37    51.5 1851.31      60 1850.08
    64.2 1849.71    75.7 1849.46    85.5 1847.72    93.1 1845.97    94.71845.791
    98.9 1845.46   101.11845.817   105.8 1847.27   108.1 1847.63   113.1 1847.76
   128.2 1848.84   142.7 1850.04   153.8 1851.22   170.9  1852.3   177.2 1852.49
   187.5 1852.44   191.7 1852.71   206.5 1854.73   228.9  1857.1   234.8 1857.45
#Mann= 3 ,-1,0
       0      .1       0    94.7    .045       0   101.1      .1       0
Bank Sta=94.7,101.1
XS Rating Curve= 0 ,0
Exp/Cntr(USF)=0,0
Exp/Cntr=0.3,0.1

Type RM Length L Ch R = 1 ,1231    ,116.4,119.8,120.5
XS GIS Cut Line= 3
2196029.12498847 657052.898514832196087.92735039657166.634662217
2196145.95599701657373.990359495
#Sta/Elev= 30
       0 1846.77    15.4 1846.62    29.2 1847.43      44 1847.36      47 1846.77
    54.4 1843.55    58.11842.608    70.4 1842.62    79.6 1843.32    90.4  1842.8
   103.9 1842.93   112.9 1845.88   121.9 1846.73     128 1846.75     139  1845.3
   151.4 1840.28   155.6 1838.98   159.8  1838.4   250.4 1838.56   263.4  1838.2
   267.8 1838.49   271.9 1839.65   276.1 1842.07   284.4 1849.32   288.5 1853.83
   292.8 1857.48   296.8 1859.26   317.6 1864.38     325 1867.82   343.4 1874.42
#Mann= 3 ,-1,0
       0      .1       0    58.1    .045       0    70.4      .1       0
#XS Ineff= 2 , 0
                           128.5         1860.21
Permanent Ineff=
       F       T
Bank Sta=58.1,70.4
XS Rating Curve= 0 ,0
Exp/Cntr(USF)=0,0
Exp/Cntr=0.3,0.1

Type RM Length L Ch R = 1 ,1111    ,116.2,123.8,128.1
XS GIS Cut Line= 2
2195950.20602906657114.795737898 2196033.7672802657378.632651225
#Sta/Elev= 30
       0 1843.65    15.1 1844.08    19.3 1843.77    23.5 1842.85    32.41839.497
    36.1 1839.01    40.3 1839.13    43.41839.548    51.3 1840.57    61.2 1840.65
    73.8 1841.47      78 1841.53    82.2 1841.28    90.6 1840.26      99 1841.43
   107.4 1841.52     115 1840.59   121.4 1839.13   129.6 1838.53   187.1 1838.27
   195.5 1838.04   212.3 1838.52   233.3 1838.25   241.7 1838.45   245.9 1838.85
   250.1 1841.15   264.8 1850.55     271 1854.79   275.2 1856.69   276.8 1856.95
#Mann= 3 ,-1,0
       0      .1       0    32.4    .045       0    43.4      .1       0
#XS Ineff= 2 , 0
                          103.38         1849.13
Permanent Ineff=
       F       T
Bank Sta=32.4,43.4
XS Rating Curve= 0 ,0
Exp/Cntr(USF)=0,0
Exp/Cntr=0.3,0.1

Type RM Length L Ch R = 1 ,987     ,76.1,79.6,82.3
XS GIS Cut Line= 4
2195921.83116262 657102.510283622195872.84134889 657169.06652331
2195862.00248619657256.3856356662195908.42540349657430.471575544
#Sta/Elev= 30
       0 1842.04    23.2 1839.83      43 1839.23    57.9 1837.36    82.8  1837.3
   106.9 1836.51     115 1837.02     1231834.797   123.1 1834.77   127.1 1833.81
   131.1 1833.43   137.2  1834.7   137.31834.733   143.2 1836.73   151.3 1837.32
   159.3 1839.55   167.4 1840.51   175.6 1840.39   183.9 1839.31   192.2 1839.96
   270.8 1838.42   279.1 1838.38   283.2 1838.83   287.4 1841.24   295.6 1847.13
   299.8 1848.97   320.5 1850.52   324.6 1852.38   333.2 1857.41   350.8 1863.54
#Mann= 3 ,-1,0
       0      .1       0   123.1    .045       0   137.2      .1       0
#XS Ineff= 2 , 0
          112.45 1839.11
Permanent Ineff=
       F       F
Bank Sta=123,137.3
XS Rating Curve= 0 ,0
Exp/Cntr(USF)=0,0
Exp/Cntr=0.3,0.1

Type RM Length L Ch R = 1 ,908     ,27.8,28.5,29
XS GIS Cut Line= 4
 2195910.7881833657100.4845307332195814.55544909657135.998992169
 2195754.9828041657286.6490463222195760.71094304657416.104986392
#Sta/Elev= 30
       0 1841.39       7 1840.54    15.6 1840.49    24.4  1839.3    36.9 1838.91
    49.7 1837.81    74.2 1837.17    82.9 1837.24   102.6 1835.77   112.4 1835.94
   116.7 1835.81   125.4 1834.94     134 1834.95   141.7 1833.61   151.2 1832.95
   157.7 1831.74     167 1831.36   174.3 1831.64     177 1832.02   198.5 1832.87
     220 1835.22   232.9 1835.39   237.2 1835.86   245.8 1837.51   254.4 1838.46
   291.5 1839.51   323.2    1840   335.2 1840.99   367.2 1845.48   394.2  1848.4
#Mann= 3 ,-1,0
       0      .1       0   157.7    .045       0   174.3      .1       0
Bank Sta=157.7,174.3
XS Rating Curve= 0 ,0
Exp/Cntr(USF)=0,0
Exp/Cntr=0.3,0.1

Type RM Length L Ch R = 1 ,879     ,51.6,49.8,48.2
XS GIS Cut Line= 4
2195895.03580121657075.8535332862195794.79336974657118.241761451
2195721.47319129657280.3480934862195727.20133023657409.804033557
#Sta/Elev= 30
       0 1839.44    85.6 1835.53    98.7 1835.39   108.8 1836.14   116.4 1835.39
   129.6 1834.81   137.2 1834.27   164.7 1833.44   169.1 1832.63   172.5 1831.59
   173.5 1831.25   177.9 1830.78   182.3 1830.71   188.6 1831.41   195.5 1832.39
   215.8 1833.22     237 1833.27   265.7 1835.08   270.5 1835.16   282.3 1834.71
   299.6 1835.15   311.6  1835.2   323.6 1834.82   339.6 1834.73   343.8 1835.64
   347.6 1836.75   371.7  1840.4   393.7 1844.53   403.7 1845.96   416.3 1847.34
#Mann= 3 ,-1,0
       0      .1       0   172.5    .045       0   188.6      .1       0
Bank Sta=172.5,188.6
XS Rating Curve= 0 ,0
Exp/Cntr(USF)=0,0
Exp/Cntr=0.3,0.1

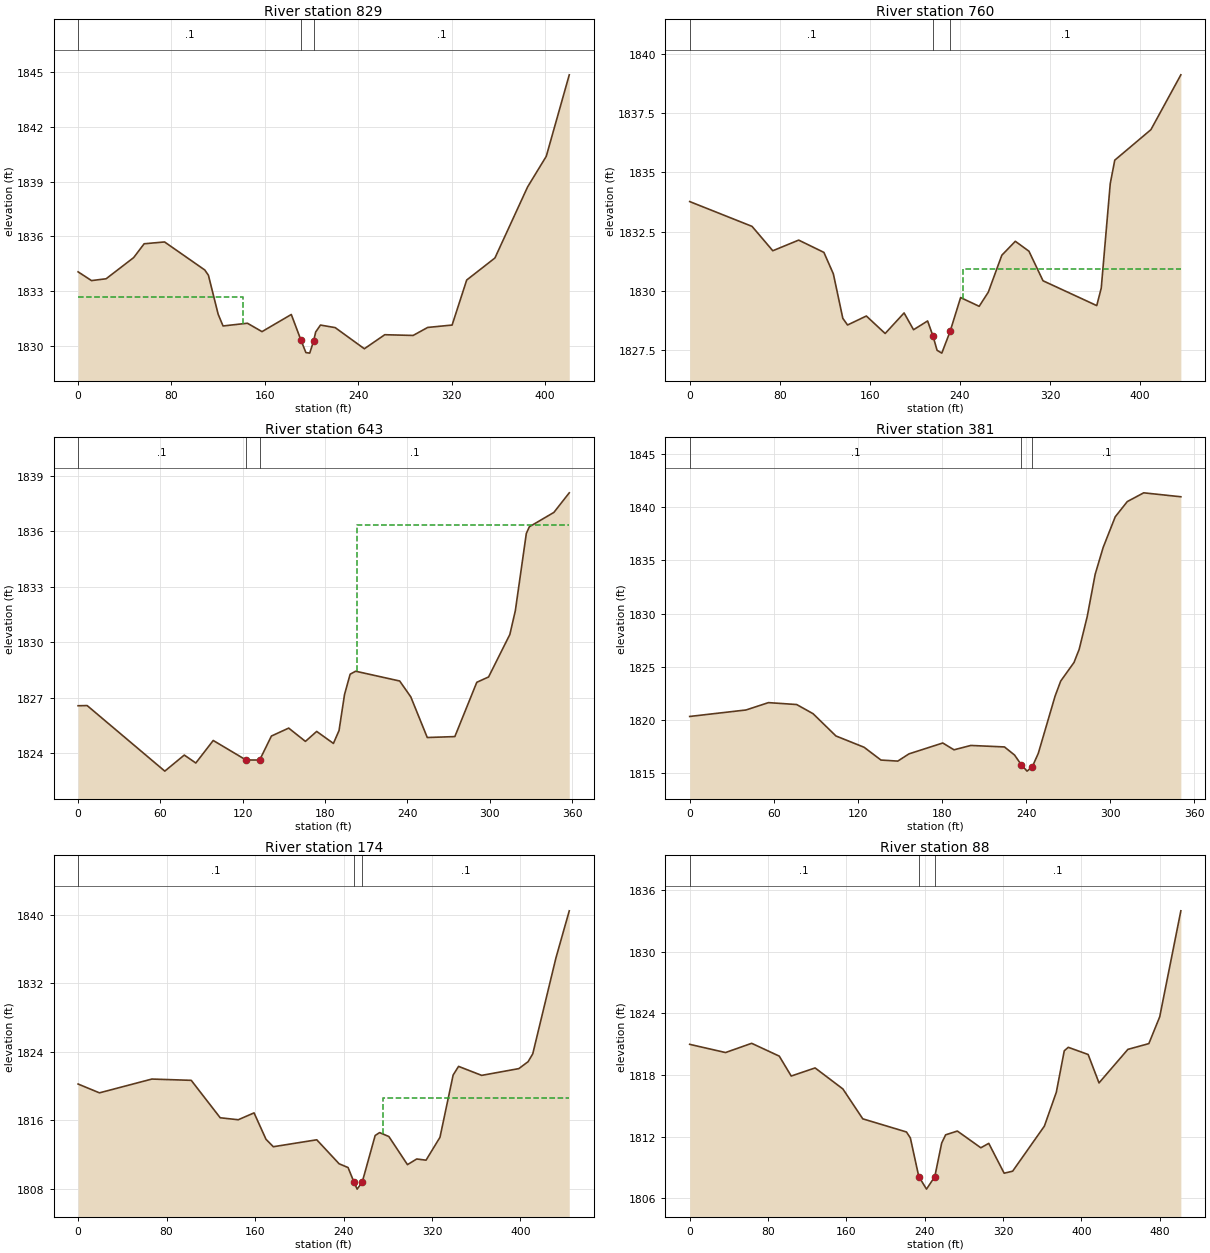
Type RM Length L Ch R = 1 ,829     ,69.5,69.9,69.8
XS GIS Cut Line= 3
2195772.45362787656986.2081588572195675.64807976657308.702381245
2195673.35682419 657392.90602368
#Sta/Elev= 30
       0 1834.05    11.5 1833.57      24 1833.67    47.6 1834.83    56.6 1835.59
    74.1 1835.69   108.6 1834.15   111.7 1833.86     120 1831.73   124.2 1831.08
   145.1 1831.23   157.6 1830.77   182.7 1831.71     191  1830.3   195.2 1829.62
   198.5 1829.59   201.8 1830.25   203.6 1830.75   207.7 1831.13   220.3 1830.99
   245.3 1829.83   262.8  1830.6   287.1 1830.56   299.6    1831   320.5 1831.13
     333  1833.6   357.2 1834.81   385.2 1838.71   401.2 1840.39   420.9 1844.86
#Mann= 3 ,-1,0
       0      .1       0     191    .045       0   201.8      .1       0
#XS Ineff= 2 , 0
          141.13 1832.65
Permanent Ineff=
       F       F
Bank Sta=191,201.8
XS Rating Curve= 0 ,0
Exp/Cntr(USF)=0,0
Exp/Cntr=0.3,0.1

Type RM Length L Ch R = 1 ,760     ,123.4,116.8,111
XS GIS Cut Line= 4
2195737.51198033656952.984952998 2195681.3762187 657052.08175668
2195640.70643222657183.8289523272195625.81327097657367.702212339
#Sta/Elev= 30
       0 1833.77    55.4 1832.72    73.8 1831.69    96.8 1832.14   119.2 1831.62
   127.6 1830.71     136 1828.83   140.2 1828.55   156.9 1828.93   173.6 1828.19
   190.4 1829.06   198.8 1828.35   211.3 1828.72   216.1 1828.08   219.7 1827.48
   223.9 1827.36   231.31828.281   240.6 1829.71   257.1 1829.34   265.2 1829.94
   277.2  1831.5   289.2 1832.09   301.3 1831.67   313.8 1830.42   361.5 1829.37
   365.5 1830.11   373.5 1834.53   377.5 1835.52   409.6 1836.81   436.2 1839.13
#Mann= 3 ,-1,0
       0      .1       0   216.1    .045       0   231.3      .1       0
#XS Ineff= 2 , 0
                           243.1          1830.9
Permanent Ineff=
       F       F
Bank Sta=216.1,231.3
XS Rating Curve= 0 ,0
Exp/Cntr(USF)=0,0
Exp/Cntr=0.3,0.1

Type RM Length L Ch R = 1 ,643     ,257.7,261.5,262.7
XS GIS Cut Line= 4
2195496.89596271657012.0610843432195546.84889244657156.529154579
2195555.54085319657202.209710414  2195568.404926657360.321715203
#Sta/Elev= 30
       0 1826.56     6.6 1826.57    63.2 1823.02    77.4 1823.89    85.8 1823.46
    98.5 1824.68   122.41823.623   132.4 1823.62   132.4 1823.63   140.9 1824.92
   153.5 1825.35   165.7 1824.63   173.9 1825.17   186.1 1824.52   190.2 1825.22
   194.2 1827.17   198.3 1828.27   202.3 1828.43   234.4  1827.9   242.5 1827.04
   254.5 1824.84   274.6 1824.89   290.6 1827.83   299.2 1828.12   314.7 1830.42
   318.7 1831.71   326.7 1835.89   328.9 1836.25   346.8 1837.03     358 1838.09
#Mann= 3 ,-1,0
       0      .1       0   122.4    .045       0   132.4      .1       0
#XS Ineff= 2 , 0
                          203.04         1836.36
Permanent Ineff=
       F       F
Bank Sta=122.4,132.4
XS Rating Curve= 0 ,0
Exp/Cntr(USF)=0,0
Exp/Cntr=0.3,0.1

Type RM Length L Ch R = 1 ,381     ,202.8,207.3,208.4
XS GIS Cut Line= 4
2195330.98895896657037.0569568252195344.14920449657248.464422893
2195346.47406419657303.013207639 2195396.3254199657370.504116318
#Sta/Elev= 30
       0 1820.35    40.2 1820.96    56.2 1821.65    76.3 1821.47      88 1820.61
   104.3 1818.52   124.4 1817.46   136.4 1816.26   148.4 1816.16   156.4 1816.84
   180.5 1817.86   188.5 1817.22   200.5 1817.63   224.5 1817.49   231.7 1816.73
   236.41815.834   240.6 1815.22   244.31815.618   248.6 1816.88   260.6 1822.26
   264.6 1823.67   274.1 1825.42   277.8 1826.66   283.5 1829.72   289.2  1833.7
   294.9 1836.22   303.5 1839.09   312.1 1840.52   323.8 1841.34   350.3 1840.97
#Mann= 3 ,-1,0
       0      .1       0   236.4    .045       0   244.3      .1       0
Bank Sta=236.4,244.3
XS Rating Curve= 0 ,0
Exp/Cntr(USF)=0,0
Exp/Cntr=0.3,0.1

Type RM Length L Ch R = 1 ,174     ,85.7,85.7,85.7
XS GIS Cut Line= 4
2195254.26316348  657011.45950342195168.89741185657206.442640655
2195157.25662753657267.5567583032195208.67009158657428.587607976
#Sta/Elev= 30
       0 1820.22    19.3 1819.19    66.7  1820.8   102.3 1820.65   128.5 1816.28
   144.8 1816.05   159.1 1816.85   169.9 1813.77   176.5  1812.9   215.8 1813.71
     236 1810.91   244.1 1810.47   249.41808.783   252.3 1807.95   256.9 1808.77
   268.6 1814.21   272.6 1814.55     281 1814.09   297.8 1810.81   306.2 1811.47
   314.6 1811.33   327.2    1814   339.1 1821.27     344 1822.28   364.9 1821.23
   398.5 1822.02   406.9 1822.83   411.1 1823.75   432.1 1834.97   444.1 1840.44
#Mann= 3 ,-1,0
       0      .1       0   249.4    .045       0   256.9      .1       0
#XS Ineff= 2 , 0
                          275.77         1818.61
Permanent Ineff=
       F       F
Bank Sta=249.4,256.9
XS Rating Curve= 0 ,0
Exp/Cntr(USF)=0,0
Exp/Cntr=0.3,0.1

Type RM Length L Ch R = 1 ,88      ,,,
XS GIS Cut Line= 6
2195088.33630005656962.034166127 2195081.8657142657044.534135718
2195104.83724036657176.6196536232195104.53748721 657256.35399295
2195130.94145312 657409.618369352195150.66421825657455.108984385
#Sta/Elev= 30
       0 1820.99    36.6 1820.19    63.3 1821.09    91.5 1819.84   103.7  1817.9
   128.1 1818.69   156.5 1816.64   176.8 1813.73   221.4 1812.45   225.4 1811.87
     234 1808.11   241.9 1806.88  250.34 1808.09   257.4 1811.37   261.4 1812.17
   273.4 1812.54   297.4 1810.91   305.5 1811.34   321.2 1808.43   329.9 1808.63
   362.3 1813.02   374.5 1816.32   382.6 1820.36   386.7  1820.7     407    1820
   418.1 1817.23   447.6  1820.5     469 1821.06   480.1 1823.67   501.7    1834
#Mann= 3 ,0,0
       0      .1       0     234    .045       0  250.34      .1       0
Bank Sta=234,250.34
XS Rating Curve= 0 ,0
Exp/Cntr(USF)=0,0
Exp/Cntr=0.3,0.1
LCMann Table=0

Chan Stop Cuts=-1
Use User Specified Reach Order=0
Composite Channel Slope=5